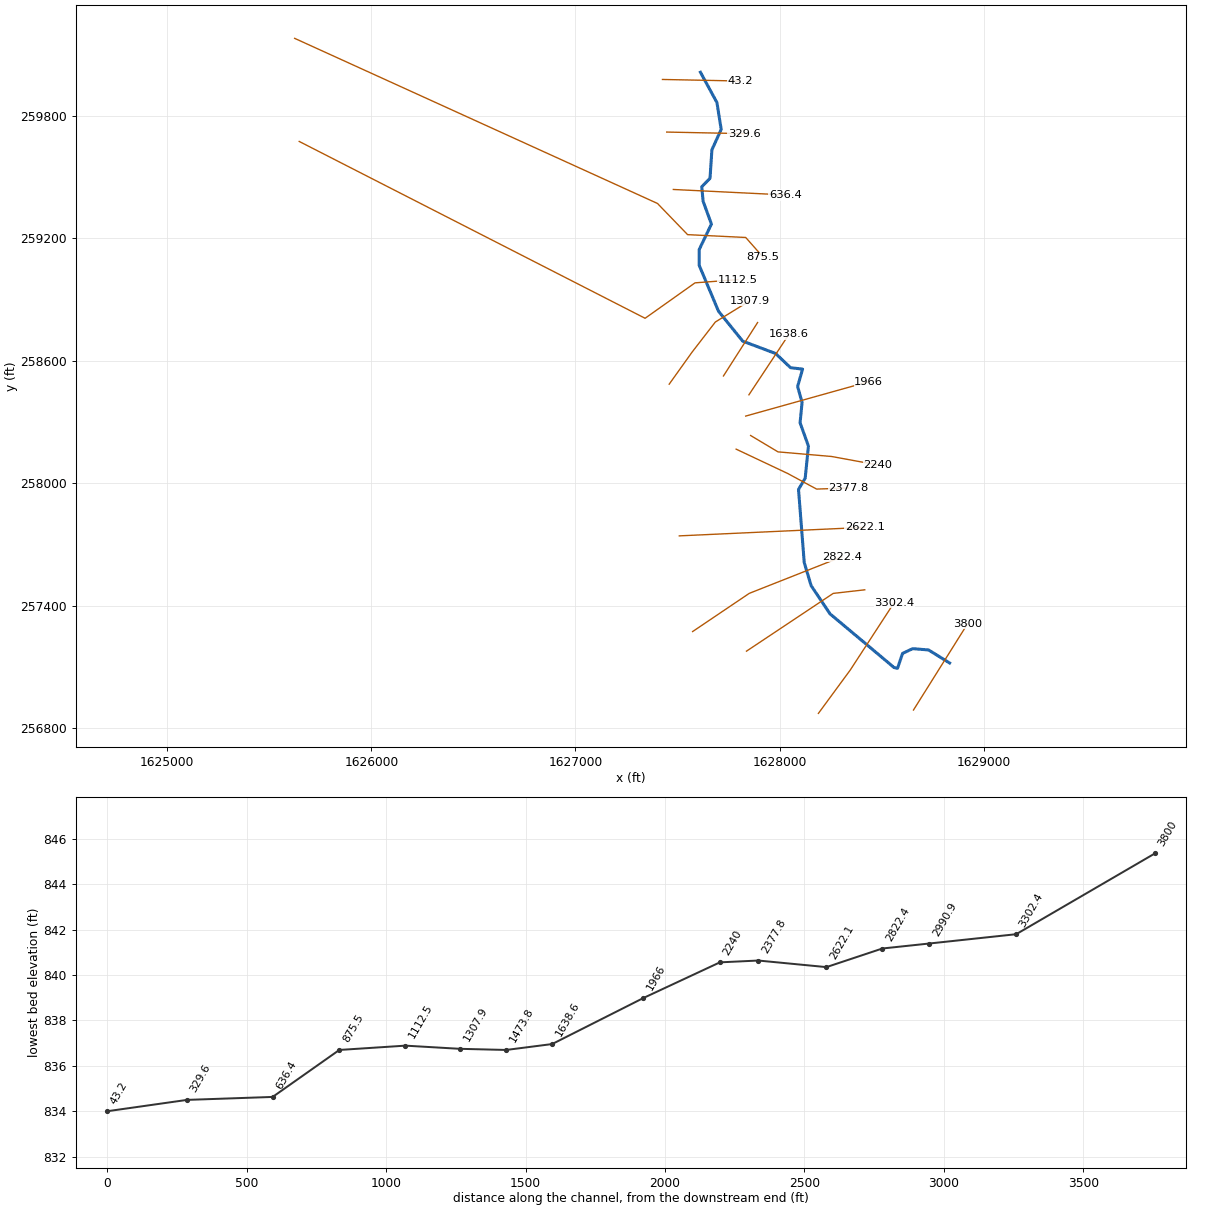
--- TOMSFRK.prj (project) ---

Proj Title=TOMSFRK
Current Plan=p01
Default Exp/Contr=0,0
English Units
Geom File=g01
Flow File=f01
Plan File=p01
BEGIN DESCRIPTION:
END DESCRIPTION:
DSS Export Rating Curves= 0
DSS Export Rating Curve Sorted= 0
DSS Export Volume Flow Curves= 0
DXF OffsetX= 0
DXF OffsetY= 0
DXF ScaleX= 0
DXF ScaleY= 0

--- TOMSFRK.p01 (plan) ---

Plan Title=Floodplain
Program Version=4.00
Geom File=g01
Flow File=f01
K Sum by GR=0
Std Step Tol=0.01
Critical Tol=0.01
Num of Std Step Trials=20
Max Error Tol=0.3
Flow Tol Ratio=0.001
Split Flow NTrial=30
Split Flow Tol=0.02
Split Flow Ratio=0.02
Log Output Level=0
Friction Slope Method=1
Unsteady Friction Slope Method=2
Unsteady Bridges Friction Slope Method=1
Global Log Level=0
CheckData=False
Run HTab=0
Run UNet=0
Run PostProcess=0
UNET Theta=0
UNET Theta Warmup=0
UNET ZTol=0
UNET ZSATol=0
UNET MxIter=0
UNET MaxInSteps=0
UNET DtIC=0
UNET DtMin=0
UNET MaxCRTS=0
UNET WFStab=0
UNET SFStab=0
UNET WFX=0
UNET SFX=0
UNET DSS MLevel=0
UNET DZMax Abort=0
UNET Convert EG Bridges=0
UNET Use Existing IB Tables=0
UNET Froude Limit=0
UNET Froude Power=0
Write IC File=0
Echo Input=False
Echo Output=False
Write Detailed=0

--- TOMSFRK.f01 (steady flow) ---

Flow Title=NFF Regression Equation
Program Version=4.10
Number of Profiles= 1
Profile Names=P100yr
River Rch & RM=TOMSFRK,Main            ,3800
2067.746
River Rch & RM=TOMSFRK,Main            ,1112.5
2191.652
River Rch & RM=TOMSFRK,Main            ,875.5
3111.214
River Rch & RM=TOMSFRK,Main            ,329.6
3119.667
Boundary for River Rch & Prof#=TOMSFRK,Main            , 1
Up Type= 0
Dn Type= 1
Dn Known WS=843
DSS Import GetInterval= 0
DSS Import GetPeak= 0
DSS Import FillOption= 0

--- TOMSFRK.g01 (geometry) ---

Geom Title=USGS 10m DEM
Program Version=4.10

River Reach=TOMSFRK         ,Main
Reach XY= 30
     1628832.919      257119.303     1628730.054      257183.105
     1628651.929      257189.615      1628602.45      257166.178
      1628577.71      257093.261     1628560.783      257097.167
     1628246.981      257360.188     1628154.533      257498.209
     1628120.679       257611.49     1628092.728      257969.737
     1628125.367      258024.598     1628141.339      258182.237
     1628100.366      258296.125     1628110.089      258396.126
     1628088.329      258474.019     1628112.635      258559.088
     1628053.607      258566.033      1627980.69      258635.477
     1627819.232      258696.241     1627700.742      258842.726
     1627606.125      259067.552     1627606.125      259144.809
      1627666.02      259269.809     1627625.222      259381.788
      1627618.63       259452.48      1627659.15      259494.014
     1627668.264      259633.336     1627713.837      259733.597
     1627693.004      259865.107     1627612.275      260013.545

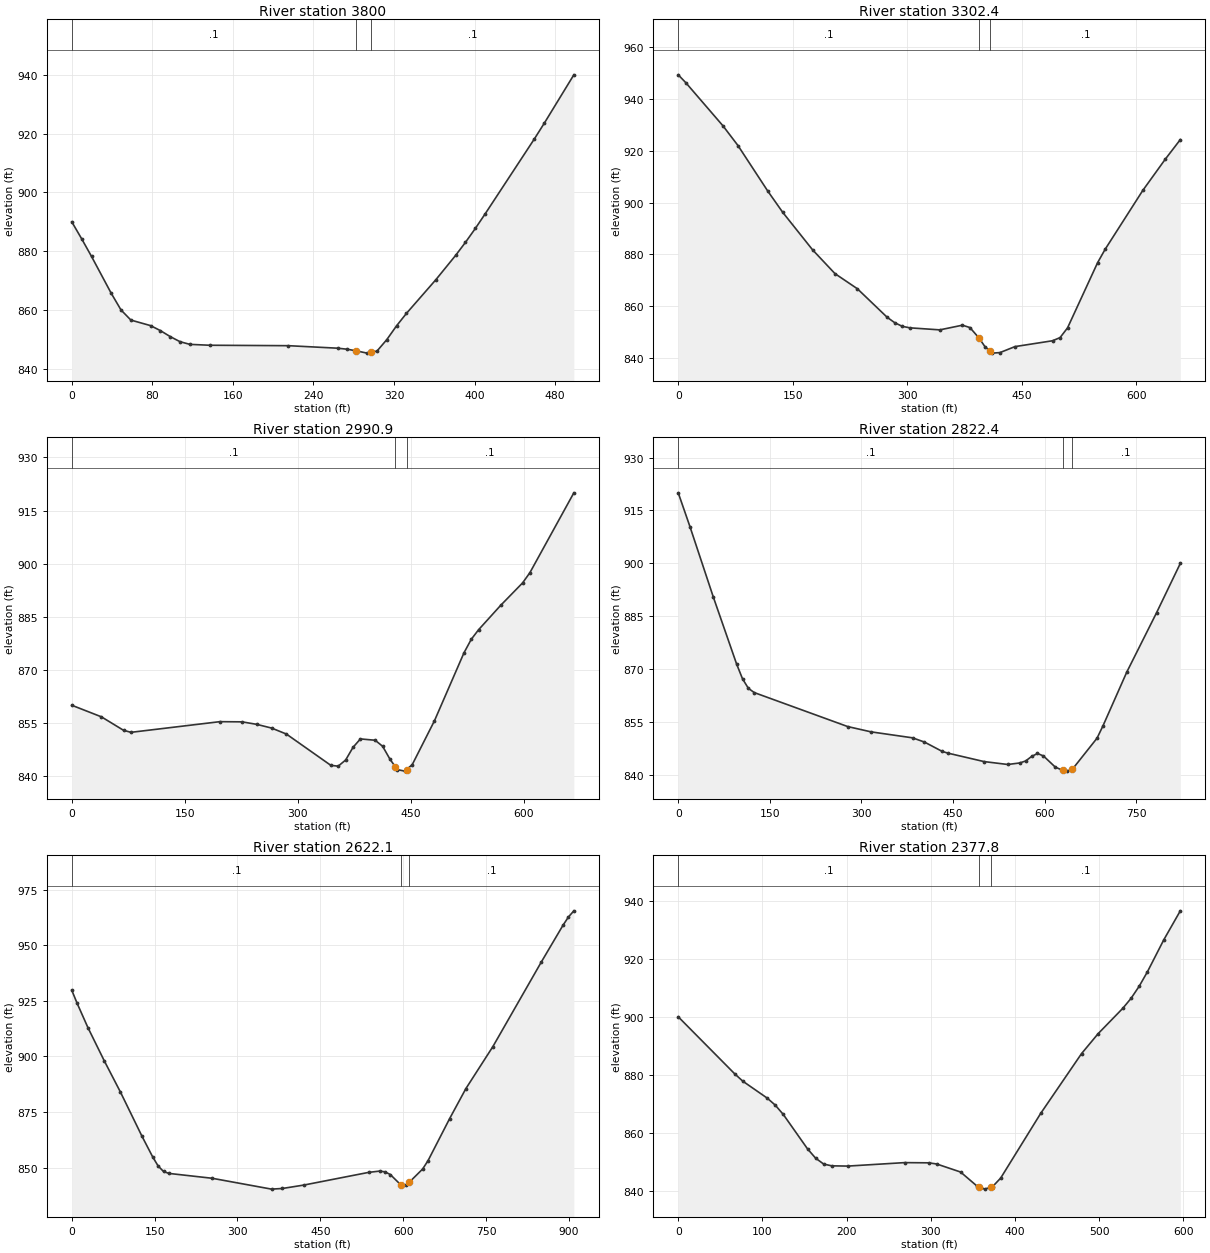
Type RM Length L Ch R = 1 ,3800    ,500.7,497.6,484.1
XS GIS Cut Line= 2
     1628655.928      256888.871     1628920.841      257311.262
#Sta/Elev= 30
       0  890.01     9.8  884.25    19.6  878.25    39.1  865.76    48.9  860.04
    58.7   856.6    78.2  854.72      88  853.02    97.8  850.98   107.5  849.25
   117.3  848.34   136.9  848.04   215.1  847.89     264  847.04   273.7  846.68
   282.4  846.14   293.3  845.36   297.4  845.65   303.1  846.05   312.8  849.93
   322.6  854.67   332.4  858.89   361.7  870.38   381.3  878.64     391  883.05
   400.8  887.77   410.6  892.76   459.5  918.26   469.3  923.58   498.6     940
#Mann= 3 , 0 , 0
       0      .1       0   282.4    .045       0   297.4      .1       0
Bank Sta=282.4,297.4
XS Rating Curve= 0 ,0
Exp/Cntr=0.3,0.1

Type RM Length L Ch R = 1 ,3302.4  ,320.7,311.5,302.4
XS GIS Cut Line= 3
     1628190.183      256872.486     1628346.433      257085.159
     1628561.277       257415.02
#Sta/Elev= 30
       0  949.38     9.8  946.38    58.6  929.66    78.2  922.06   117.3  904.43
   136.8  896.25   175.9  881.75   205.3  872.53   234.6  866.69   273.7  855.64
   283.6  853.55   293.4  852.16   303.3  851.58   342.6  850.79   372.2   852.6
     382  851.69   393.9  847.67   401.7  844.31   408.9  842.47   411.5   841.8
   421.4  842.01     441  844.32   490.2  846.58   500.1   847.8   509.9  851.56
   549.3  876.78   559.1  881.92   608.4  904.67   637.9  916.76   657.6  924.34
#Mann= 3 , 0 , 0
       0      .1       0   393.9    .045       0   408.9      .1       0
Bank Sta=393.9,408.9
XS Rating Curve= 0 ,0
Exp/Cntr=0.3,0.1

Type RM Length L Ch R = 1 ,2990.9  ,173.2,168.4,163.7
XS GIS Cut Line= 3
     1627837.725       257177.23     1628262.781      257460.279
     1628417.312       257477.83
#Sta/Elev= 30
       0     860    39.3  856.73    68.7  852.92    78.6  852.35   196.4  855.36
   225.9  855.31   245.5   854.6   265.2  853.55   284.8  851.86   343.7  843.03
   353.5  842.79   363.4  844.53   373.2  848.11     383  850.49   402.6  850.11
   412.5   848.4   422.3  844.73   429.3  842.64   432.1  841.81   441.9  841.39
   444.3  841.84   451.8  843.24   481.2  855.59   520.4   874.8   530.1  878.63
   539.8  881.33     569  888.19   598.2  894.56   607.9  897.45   666.2     920
#Mann= 3 , 0 , 0
       0      .1       0   429.3    .045       0   444.3      .1       0
Bank Sta=429.3,444.3
XS Rating Curve= 0 ,0
Exp/Cntr=0.3,0.1

Type RM Length L Ch R = 1 ,2822.4  ,207.8,200.4,192.9
XS GIS Cut Line= 3
     1627573.816      257273.276     1627851.641      257460.593
     1628304.781      257639.573
#Sta/Elev= 30
       0     920    19.2  910.42    57.4  890.51    95.7  871.46   105.3  867.31
   114.9  864.62   124.5  863.42   277.6  853.79   315.9  852.29   383.8   850.6
   403.3   849.4   432.5  846.74   442.3  846.24   500.7  843.88   539.7  843.05
   559.2  843.48   568.9  844.04   578.7  845.32   588.4  846.17   598.2  845.46
   617.6   842.3   629.7   841.4   637.1  841.17   644.7  841.81   646.9     842
   685.9   850.5   695.6  853.98   734.6  869.21   783.3     886   822.3  900.01
#Mann= 3 , 0 , 0
       0      .1       0   629.7    .045       0   644.7      .1       0
Bank Sta=629.7,644.7
XS Rating Curve= 0 ,0
Exp/Cntr=0.3,0.1

Type RM Length L Ch R = 1 ,2622.1  ,256.9,244.3,231.6
XS GIS Cut Line= 2
     1627508.562      257742.143     1628416.486      257783.935
#Sta/Elev= 30
       0  929.74     9.8  923.81    29.3  912.91    58.6  898.13      88  884.03
     127  864.17   146.6  854.77   156.4  850.73   166.1  848.29   175.9  847.41
   254.1  845.23   361.6  840.35   381.2  840.64   420.2  842.18   537.5  847.88
   557.1  848.45   566.8  848.13   576.6  846.92   595.9  842.21   605.9  842.35
   610.9  843.42   635.2   849.4     645  853.18   684.1  872.07   713.4  885.51
   762.3   904.4   850.2  942.51   889.3  958.96   899.1  962.65   908.9  965.43
#Mann= 3 , 0 , 0
       0      .1       0   595.9    .045       0   610.9      .1       0
Bank Sta=595.9,610.9
XS Rating Curve= 0 ,0
Exp/Cntr=0.3,0.1

Type RM Length L Ch R = 1 ,2377.8  ,128.5,137.8,147.1
XS GIS Cut Line= 4
      1627787.22      258166.977     1628038.995      258048.178
     1628181.285      257971.444     1628337.535      257976.652
#Sta/Elev= 30
       0     900    67.2  880.32    76.8   877.8   105.6  872.01   115.2  869.59
   124.8  866.36   153.6   854.5   163.2   851.3   172.8  849.27   182.4  848.66
   201.6  848.58   268.8  849.77   297.4   849.7   306.9  849.31   335.4  846.53
   354.5  841.79   356.8  841.51     364  840.64   371.8  841.38   373.5  841.54
     383  844.44   430.6  866.75   479.1  887.33   498.7  894.16     528   902.9
   537.8  906.32   547.5   910.5   557.3  915.48   576.8  926.53   596.4   936.5
#Mann= 3 , 0 , 0
       0      .1       0   356.8    .045       0   371.8      .1       0
Bank Sta=356.8,371.8
XS Rating Curve= 0 ,0
Exp/Cntr=0.3,0.1

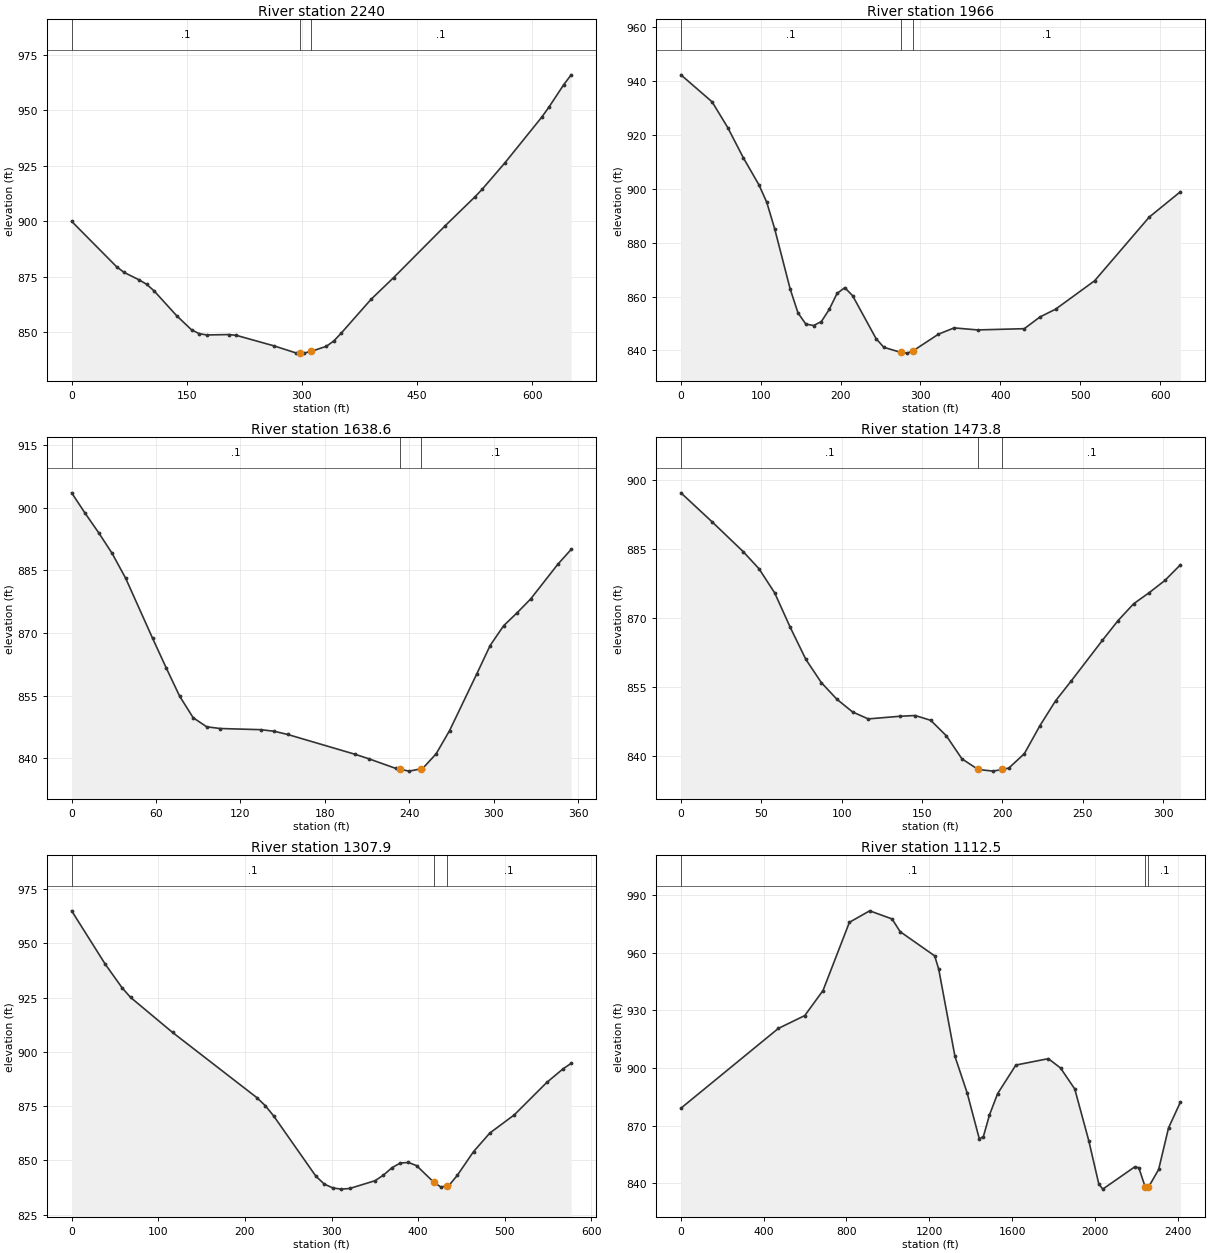
Type RM Length L Ch R = 1 ,2240    ,265.7,274,282.2
XS GIS Cut Line= 4
      1627858.01       258233.98     1627992.049      258153.736
     1628254.202      258131.166     1628481.632        258089.5
#Sta/Elev= 30
       0     900    58.6  879.51    68.4  876.96    87.9   873.6    97.6  871.63
   107.4  868.64   136.7  857.47   156.2  851.06     166  849.37   175.7  848.76
     205  848.93   214.7  848.56   263.4  843.85   292.7  840.59   297.1  840.58
   302.4  840.56   312.1  841.37   331.6  843.62   341.4  846.01   351.1  849.58
   390.1  864.88   419.4  874.64   486.8  898.11   525.3  911.06     535  914.59
   563.9  926.22     612  946.87   621.7  951.55   640.9  961.64   650.6  966.09
#Mann= 3 , 0 , 0
       0      .1       0   297.1    .045       0   312.1      .1       0
Bank Sta=297.1,312.1
XS Rating Curve= 0 ,0
Exp/Cntr=0.3,0.1

Type RM Length L Ch R = 1 ,1966    ,309.6,327.4,345.2
XS GIS Cut Line= 2
     1627834.063      258329.083     1628436.494      258497.486
#Sta/Elev= 30
       0  942.25    39.1  932.21    58.6   922.7    78.2  911.45    97.7  901.43
   107.5  894.95   117.3  885.23   136.8   862.8   146.6  853.92   156.4  849.78
   166.2  849.23   175.9  850.72   185.7   855.2   195.5  861.13   205.2  863.28
     215   860.3   244.4  844.36   254.1  841.15   275.3  839.27   283.4  838.99
   290.3  839.76   322.5  846.02   342.1  848.35   371.4   847.6     430  848.06
   449.6  852.41   469.1  855.28     518  865.83   586.4  889.46   625.5  898.88
#Mann= 3 , 0 , 0
       0      .1       0   275.3    .045       0   290.3      .1       0
Bank Sta=275.3,290.3
XS Rating Curve= 0 ,0
Exp/Cntr=0.3,0.1

Type RM Length L Ch R = 1 ,1638.6  ,164.4,164.8,165.1
XS GIS Cut Line= 2
     1627849.688       258433.25     1628045.675      258729.376
#Sta/Elev= 30
       0  903.56     9.6  898.67    19.2  894.02    28.8  889.06    38.4  883.12
    57.6  868.71    67.2  861.69    76.8  854.88    86.4  849.74      96  847.57
   105.6  847.16   134.4  846.88     144   846.5   153.6  845.73   201.6  840.98
   211.2  839.92   230.3  837.63   233.4  837.41   239.9  836.96   248.4  837.51
   249.5  837.58   259.1   841.1   268.7  846.68   287.9  860.16   297.5  867.02
   307.1  871.76   316.7  874.86   326.3  878.16   345.5  886.42   355.1  890.02
#Mann= 3 , 0 , 0
       0      .1       0   233.4    .045       0   248.4      .1       0
Bank Sta=233.4,248.4
XS Rating Curve= 0 ,0
Exp/Cntr=0.3,0.1

Type RM Length L Ch R = 1 ,1473.8  ,174.5,166,154
XS GIS Cut Line= 2
     1627724.991      258525.597     1627892.312      258787.432
#Sta/Elev= 30
       0  897.24    19.4  890.93    38.8  884.43    48.6  880.71    58.3  875.49
      68  867.98    77.7  861.02    87.4  855.93    97.1  852.31   106.8  849.57
   116.5  848.06     136  848.63   145.7   848.8   155.4  847.75   165.1  844.38
   174.8  839.37   184.9  837.06   194.2   836.7   199.9  837.08   203.9  837.35
   213.6  840.49   223.3  846.59     233  851.98   242.8  856.33   262.2  865.17
   271.9  869.45   281.6  873.11   291.3  875.53     301  878.17   310.7  881.59
#Mann= 3 , 0 , 0
       0      .1       0   184.9    .045       0   199.9      .1       0
Bank Sta=184.9,199.9
XS Rating Curve= 0 ,0
Exp/Cntr=0.3,0.1

Type RM Length L Ch R = 1 ,1307.9  ,206.3,195.3,184.5
XS GIS Cut Line= 4
     1627459.063      258485.333      1627571.91      258643.319
     1627685.178       258789.86      1627853.16      258893.319
#Sta/Elev= 30
       0  964.96    38.8  940.38    58.2  929.52      68  925.09   116.5  908.94
   213.6  878.96   223.4  875.25   233.1  870.52   281.9  842.73   291.6  839.09
   301.4  837.31   311.1  836.75   320.9  837.04   350.1  840.62   359.9  843.19
   369.6  846.57   379.4  848.78   388.8  849.03   398.2  847.56   418.2  839.86
   426.3  837.71   433.2   838.3   435.7  838.52   445.1  843.08   463.9  854.02
   482.7  862.59   510.9  870.95   548.5  885.92   567.2  892.16   576.6  894.69
#Mann= 3 , 0 , 0
       0      .1       0   418.2    .045       0   433.2      .1       0
Bank Sta=418.2,433.2
XS Rating Curve= 0 ,0
Exp/Cntr=0.3,0.1

Type RM Length L Ch R = 1 ,1112.5  ,239.5,237,234.2
XS GIS Cut Line= 4
     1625646.563      259674.569     1627341.007       258808.25
     1627585.799      258981.861     1627795.869      258997.486
#Sta/Elev= 30
       0     879   470.9  920.53   598.4   927.2   686.7  940.25   814.2  975.76
   912.3  981.72  1020.2   977.5  1059.4  970.88  1226.2  958.28  1245.8  951.32
  1324.3  905.93  1383.2  886.97    1442  863.03  1461.6  864.27  1491.1   875.5
  1530.3  886.57  1618.6  901.46  1775.5  904.79  1834.4  899.92  1903.1  889.01
  1970.8  862.13  2019.2   839.6  2038.6  836.89  2193.5  848.52  2212.7  848.01
  2243.5  838.01  2258.5  837.74  2308.5  847.12  2356.4   868.8  2413.8  882.21
#Mann= 3 , 0 , 0
       0      .1       0  2243.5    .045       0  2258.5      .1       0
Bank Sta=2243.5,2258.5
XS Rating Curve= 0 ,0
Exp/Cntr=0.3,0.1

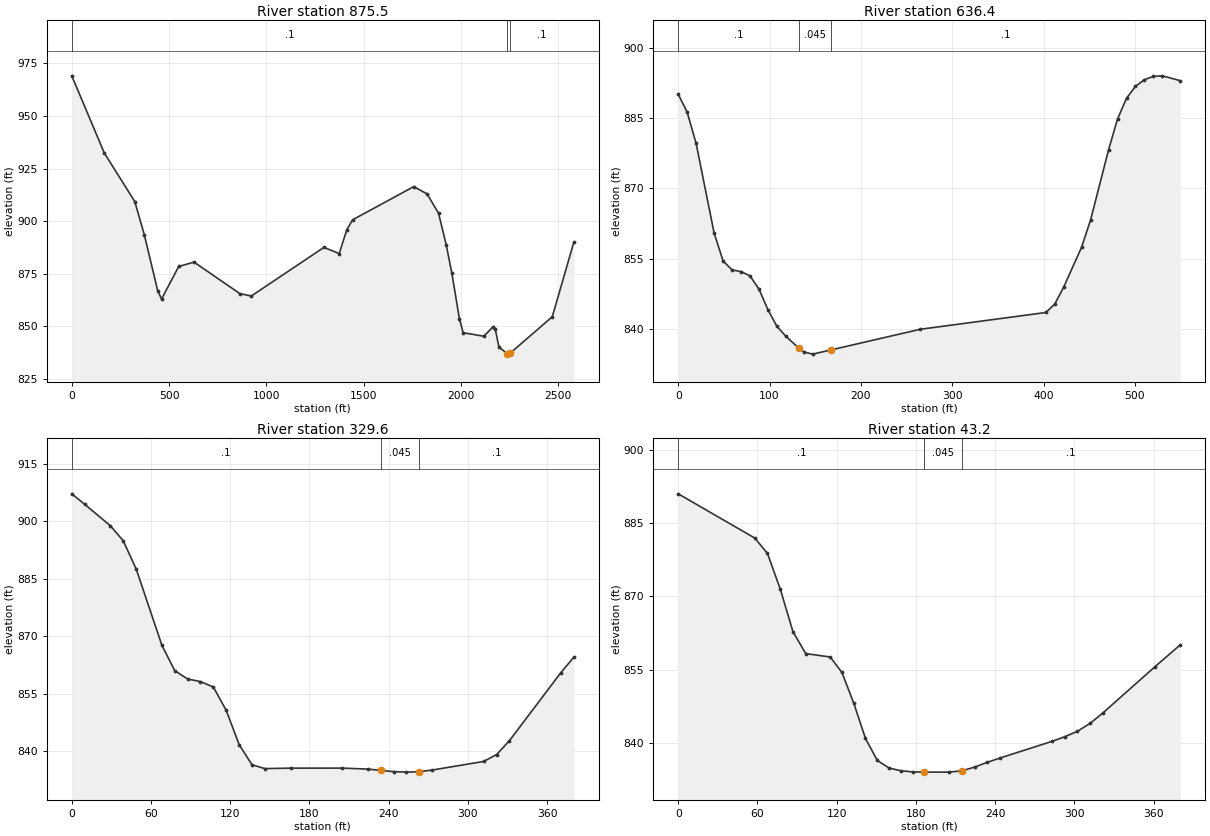
Type RM Length L Ch R = 1 ,875.5   ,239,239.1,239.3
XS GIS Cut Line= 5
     1625623.994      260179.777     1627401.771       259370.75
     1627549.341      259217.972     1627834.063      259204.083
       1627919.6      259107.417
#Sta/Elev= 30
       0  969.12   166.9  932.45   323.9  909.27     373  893.41   441.7  866.82
   461.3  862.92   549.6  878.41   628.2  880.48   863.7  865.49   922.6  864.35
  1295.6  887.48  1374.1  884.54  1413.4   895.9  1442.8  900.59  1756.9  916.39
  1825.6  912.94  1884.5  903.74  1923.8  888.84  1953.2  875.09  1991.8  853.53
  2011.1  846.89  2117.3   845.2  2165.6   849.8  2175.4  848.89  2195.1  839.98
  2238.5  836.96  2244.2   836.7  2253.5  837.22  2469.1   854.5  2579.8     890
#Mann= 3 , 0 , 0
       0      .1       0  2238.5    .045       0  2253.5      .1       0
Bank Sta=2238.5,2253.5
XS Rating Curve= 0 ,0
Exp/Cntr=0.3,0.1

Type RM Length L Ch R = 1 ,636.4   ,303.7,306.7,309.7
XS GIS Cut Line= 2
     1627479.445      259439.307     1628028.507      259412.416
#Sta/Elev= 30
       0  890.06     9.8  886.23    19.6  879.56    39.3  860.44    49.1  854.51
    58.9  852.59    68.7  852.23    78.5  851.34    88.4   848.5    98.2   844.1
     108  840.57   117.8  838.44   132.1   835.9   137.4   835.1   147.1  834.63
   166.9  835.51     265  839.93   402.5  843.51   412.3  845.33   422.1  848.96
   441.7  857.47   451.6  863.34   471.2  878.25     481  884.79   490.8   889.2
   500.6  891.74   510.4  893.17   520.3  893.87   530.1  893.99   549.7  892.95
#Mann= 3 , 0 , 0
       0      .1       0   132.1    .045       0   166.9      .1       0
Bank Sta=132.1,166.9
XS Rating Curve= 0 ,0
Exp/Cntr=0.3,0.1

Type RM Length L Ch R = 1 ,329.6   ,290.6,286.4,282.7
XS GIS Cut Line= 2
      1627446.91      259720.576     1627827.119      259712.764
#Sta/Elev= 27
       0  907.14     9.8   904.4    29.2  898.82      39  894.87    48.8  887.52
    68.3  867.58      78  860.99    87.8   858.8    97.5  858.14   107.3  856.69
     117  850.61   126.8  841.66   136.5  836.43   146.3  835.42   165.8  835.54
   204.8  835.55   224.3  835.29     234  834.97   243.7  834.63   253.5   834.5
   263.3  834.61     273  835.04     312  837.29   321.8  839.08   331.5   842.7
   370.5  860.49   380.3   864.5
#Mann= 3 , 0 , 0
       0      .1       0     234    .045       0   263.3      .1       0
Bank Sta=234,263.3
XS Rating Curve= 0 ,0
Exp/Cntr=0.3,0.1

Type RM Length L Ch R = 1 ,43.2    ,40.9,43.2,45
XS GIS Cut Line= 4
     1627426.098      259978.305     1627532.313      259976.175
     1627621.337      259974.389     1627806.285      259970.576
#Sta/Elev= 27
       0  890.99      58  881.93    67.6  878.78    77.3  871.47    86.9  862.76
    96.6  858.27   115.1  857.58     124  854.41     133  848.08   141.8  840.91
   150.8  836.39   159.7  834.84   168.6  834.28   177.5  834.05   186.4     834
     205     834   214.8  834.26   224.5  835.03   234.2  836.02     244  836.91
   282.9  840.28   292.6  841.23   302.4  842.36   312.1  844.01   321.8  846.15
   360.8  855.52   380.3  860.07
#Mann= 3 , 0 , 0
       0      .1       0   186.4    .045       0   214.8      .1       0
Bank Sta=186.4,214.8
XS Rating Curve= 0 ,0
Exp/Cntr=0.3,0.1

Chan Stop Cuts=-1
Use User Specified Reach Order=0
Composite Channel Slope=5